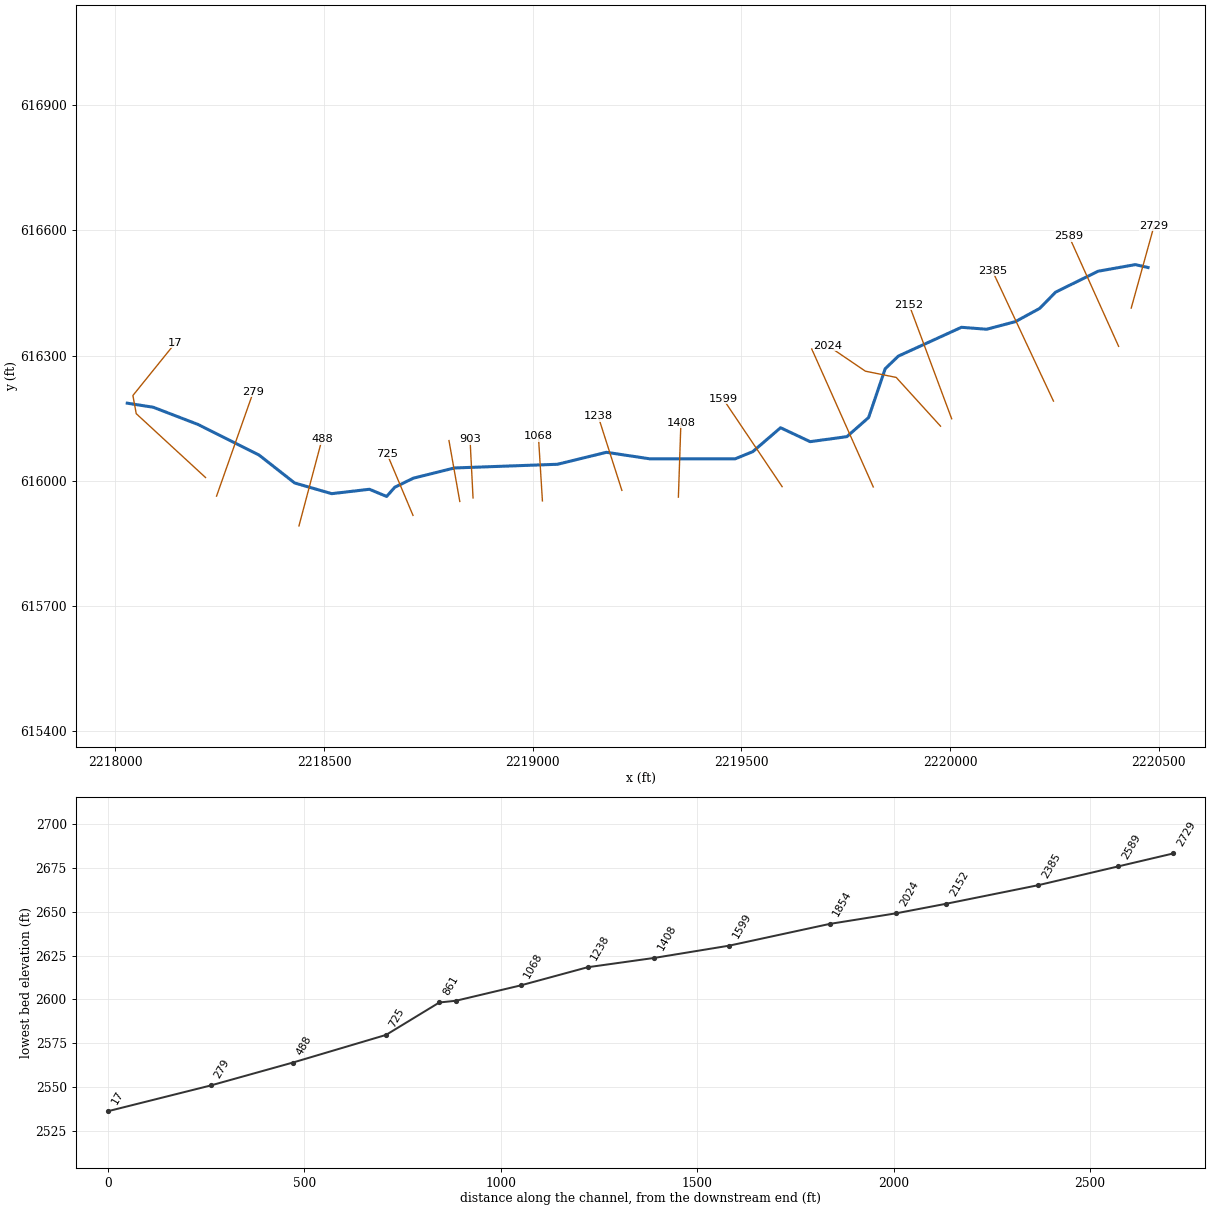
--- LICKRN.prj (project) ---

Proj Title=LICKRN
Current Plan=p01
Default Exp/Contr=0,0
English Units
Geom File=g01
Flow File=f01
Plan File=p01
BEGIN DESCRIPTION:
----------MODEL BY WOOD PLC 2022----------
AFH study
Randolph County, WV
HEC-RAS Version: RAS 6.2
Vertical Datum: NAVD88
Projection: NAD 1983 StatePlane West Virginia S FIPS 4702 (US Feet)
Terrain: 1-meter LIDAR (FEMA Region III 3DEP collected 2016-2018)
Land Use: 2019 NLCD
Hydrologic Method:
WV SIR2010-5033 regression equations
Additional Model Notes:
None
END DESCRIPTION:
DSS Export Rating Curves= 0
DSS Export Rating Curve Sorted= 0
DSS Export Volume Flow Curves= 0
DXF OffsetX= 0
DXF OffsetY= 0
DXF ScaleX= 0
DXF ScaleY= 0

--- LICKRN.p01 (plan) ---

Plan Title=Floodplain
Program Version=6.20
Short Identifier=Floodplain
Geom File=g01
Flow File=f01
Subcritical Flow
K Sum by GR= 0
Std Step Tol= 0.01
Critical Tol= 0.01
Num of Std Step Trials= 20
Max Error Tol= 0.3
Flow Tol Ratio= 0.001
Split Flow NTrial= 30
Split Flow Tol= 0.02
Split Flow Ratio= 0.02
Log Output Level= 0
Friction Slope Method= 1
Unsteady Friction Slope Method= 2
Unsteady Bridges Friction Slope Method= 1
Parabolic Critical Depth
Global Vel Dist= 0 , 0 , 0
Global Log Level= 0
CheckData=False
Encroach Param=-1 ,0,0, 0
Mapping Interval=1HOUR
Computation Time Step Use Courant=        0
Computation Time Step Use Time Series=    0
Computation Time Step Count To Double=0
Computation Time Step Max Doubling=0
Computation Time Step Max Halving=0
Computation Time Step Residence Courant=0
Run HTab= 0
Run UNet= 0
Run Sediment= 0
Run PostProcess= 0
Run WQNet= 0
Run RASMapper=-1
UNET Theta= 0
UNET Theta Warmup= 0
UNET ZTol= 0
UNET ZSATol= 0
UNET MxIter= 0
UNET Max Iter WO Improvement= 0
UNET MaxInSteps= 0
UNET DtIC= 0
UNET DtMin= 0
UNET MaxCRTS= 0
UNET WFStab= 0
UNET SFStab= 0
UNET WFX= 1
UNET SFX= 1
UNET Gravity=32.174
UNET 1D Methodology=Finite Difference
UNET DSS MLevel= 1
UNET Pardiso=0
UNET DZMax Abort= 0
UNET Use Existing IB Tables= 0
UNET Froude Reduction=False
UNET Froude Limit= 0
UNET Froude Power= 0
UNET D1 Cores= 0
UNET WindReference=Eulerian
UNET WindDragFormulation=Hsu (1988)
UNET D2 Coriolis=0
UNET D2 Cores= 0
UNET D2 Theta= 1
UNET D2 Theta Warmup= 1
UNET D2 Z Tol= 0.01
UNET D2 Volume Tol= 0.01
UNET D2 Max Iterations= 20
UNET D2 Equation= 0
UNET D2 RampUpFraction=0.1
UNET D2 TimeSlices= 1
UNET D2 Turbulence Formulation=Non-Conservative (original)
UNET D2 Eddy Viscosity=0.3
UNET D2 Transverse Eddy Viscosity=0.1
UNET D2 Smagorinsky Mixing=0
UNET D2 BCVolumeCheck=0
UNET D2 Cores=0
UNET D2 SolverType=PARDISO (Direct)
UNET D2 Minimum Iterations= 2147483647
UNET D2 Maximum Iterations= 2147483647
UNET D2 Restart Number= 10
UNET D2 Relaxation Coeff=1.3
UNET D2 SOR Precondition Iterations= 10
UNET D2 ILUT Maximum Fill= 8
UNET D2 ILUT Tolerance=1E-08
UNET D1D2 MaxIter= 0
UNET D1D2 ZTol=0.01
UNET D1D2 QTol=0.1
UNET D1D2 MinQTol=1
Write IC File= 0
Write IC File at Fixed DateTime=0
Write IC File at Sim End=0
Echo Input=False
Echo Parameters=False
Echo Output=False
Write Detailed= 0
HDF Write Warmup=0
HDF Write Time Slices=0
HDF Flush=0
HDF Compression= 1
HDF Chunk Size= 1
HDF Spatial Parts= 1
HDF Use Max Rows=0
HDF Fixed Rows= 1
Calibration Method= 0
Calibration Iterations= 20
Calibration Max Change=0.05
Calibration Tolerance=0.2
Calibration Maximum=1.5
Calibration Minimum=0.5
Calibration Optimization Method= 1
WQ AD Non Conservative
WQ ULTIMATE=-1
WQ Max Comp Step=1HOUR
WQ Output Interval=15MIN
WQ Output Selected Increments= 0
WQ Output face flow=0
WQ Output face velocity=0
WQ Output face area=0
WQ Output face dispersion=0
WQ Output cell volume=0
WQ Output cell surface area=0
WQ Output cell continuity=0
WQ Output cumulative cell continuity=0
WQ Output face conc=0
WQ Output face dconc_dx=0
WQ Output face courant=0
WQ Output face peclet=0
WQ Output face adv mass=0
WQ Output face disp mass=0
WQ Output cell mass=0
WQ Output cell source sink temp=0
WQ Output nsm pathways=0
WQ Output nsm derived pathways=0
WQ Create Restart=0
WQ Fixed Restart=0
WQ System Summary=0
WQ Write To DSS=0
Sorting and Armoring Iterations= 10
XS Update Threshold= 0.02
Bed Roughness Predictor= 0
Hydraulics Update Threshold= 0.02
Energy Slope Method= 1
Volume Change Method= 1
Sediment Retention Method= 0
Sediment TS Multiplier= 1
Warm Up Method= 0
XS Weighting Method= 0
Number of US Weighted Cross Sections= 1
Number of DS Weighted Cross Sections= 1
Upstream XS Weight=0
Main XS Weight=1
Downstream XS Weight=0
Number of DS XS's Weighted with US Boundary= 1
Upstream Boundary Weight= 1
Weight of XSs Associated with US Boundary= 0
Number of US XS's Weighted with DS Boundary= 1
Downstream Boundary Weight= 0.5
Weight of XSs Associated with DS Boundary= 0.5
Percentile Method= 0
Sediment Output Level= 3
Mass or Volume Output= 0
Output Increment Type= 1
Profile and TS Output Increment= 1
Transport Output Increment 1
XS Output Flag= 0
XS Output Increment= 10
Read HDF5 Sediment Hotstart= 0
Sediment Hotstart Type= 0
Write Gradation File= 0
Read Gradation Hotstart= 0
Write HDF5 File= 1
Write Binary Output= 1
Write DSS Sediment File= 0
DSS Sediment Output Type= 1
SV Curve= 0
Specific Gage Flag= 0
Subcell Erosion Methods= 0
Subcell Deposition Methods= 0
Advection Scheme= 1
Matrix Solver= 0
Implicit Weighting Factor= 1
Maximum Outer Loop Convergence Iterations= 5
Convergence Maximum Absolute= 0.001
Convergence RMSE= 0.0001
Grain Fractions Max Abs Error= 0.001
Max Subgrid Regions= 1
Max Subgrid Length Scale= 3.402823E+38
Initial Layer Thickness= 3.402823E+38
Min Layer Thickness= 3.402823E+38
Max Layer Thickness= 3.402823E+38
Number of Layers= 5

--- LICKRN.f01 (steady flow) ---

Flow Title=Flow
Program Version=4.00
Number of Profiles=1
Profile Names=P100yr
River Rch & RM=LICKRN,Main,2729
     377
Boundary for River Rch & Prof#=LICKRN,Main      ,1
Up Type=0
Dn Type=3
Dn Slope=0.052225

--- LICKRN.g01 (geometry) ---

Geom Title=Geometry
Program Version=6.20

River Reach=LICKRN          ,Main
Reach XY= 30
     2220474.046      616511.142      2220443.67      616518.059
     2220354.521      616502.219     2220252.763       616452.13
     2220214.671      616413.226     2220156.338      616381.455
     2220087.588      616363.225     2220027.171      616367.913
     2219876.024      616298.919      2219844.51      616268.635
     2219804.776      616151.767     2219752.692      616105.934
     2219664.671      616093.955     2219593.838      616127.288
     2219527.171      616069.996     2219484.984      616052.809
     2219280.817      616052.809      2219176.65      616068.434
     2219059.463      616039.788     2218812.588      616030.934
      2218714.15      616006.455     2218669.661      615984.698
     2218650.206      615962.688     2218608.942      615979.892
     2218518.577      615969.373     2218429.775      615994.996
     2218344.879      616061.663     2218198.525        616135.1
      2218091.06       616176.42     2218028.838       616186.12

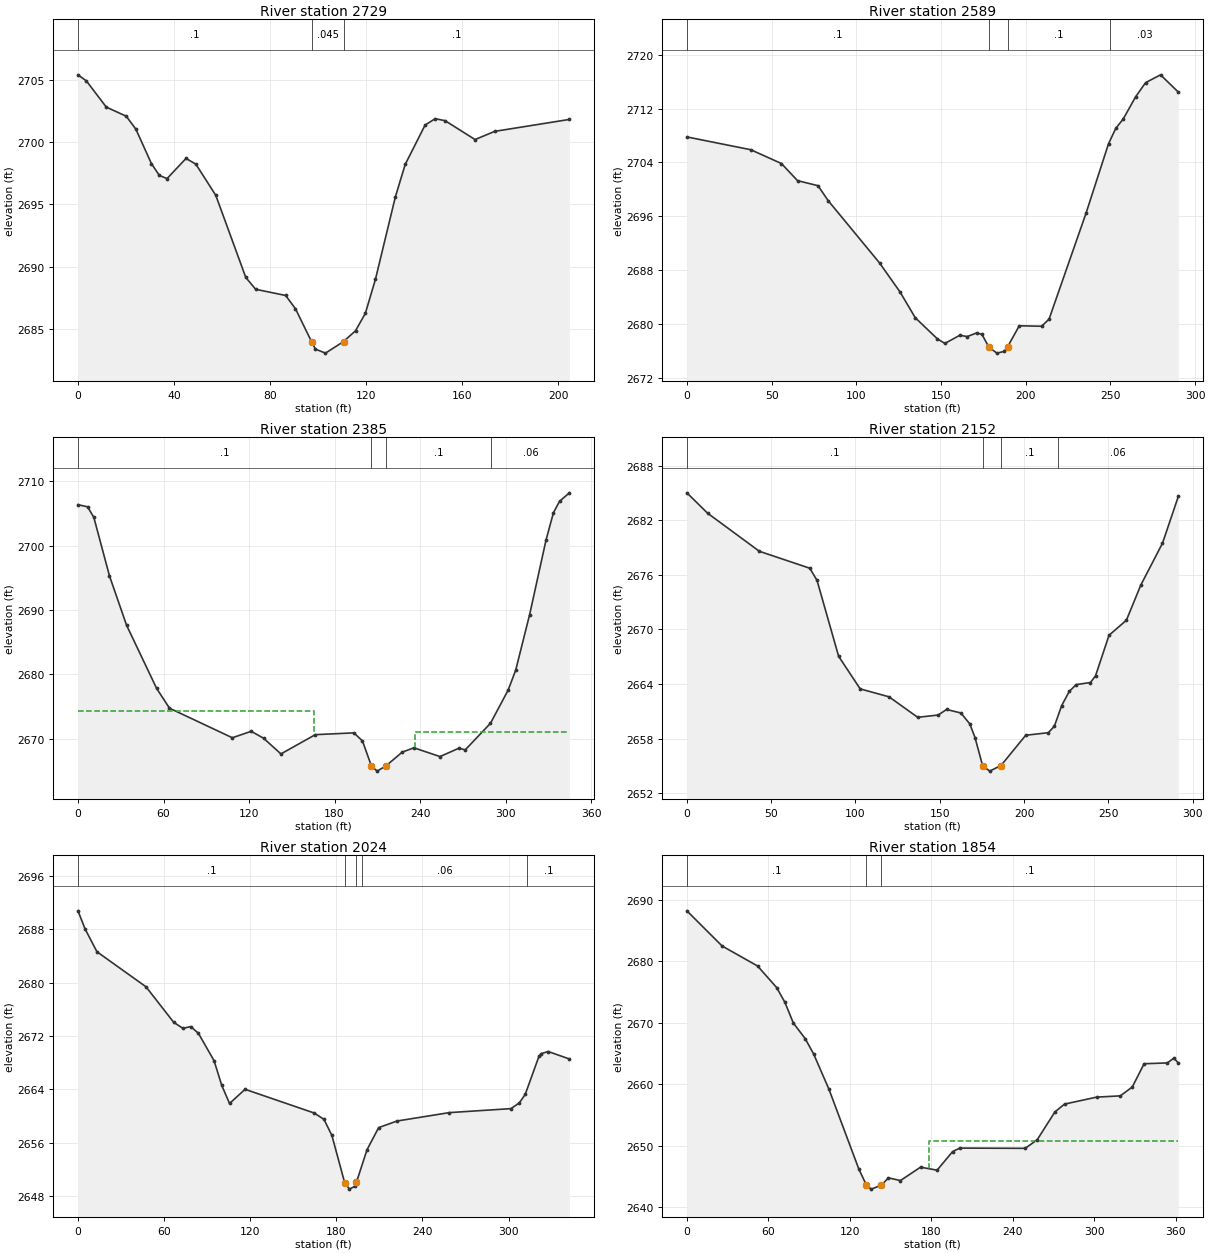
Type RM Length L Ch R = 1 ,2729    ,135.5,140,144
XS GIS Cut Line= 2
2220433.82914186616413.8420343072220488.60004649616611.041187465
#Sta/Elev= 30
       0 2705.43     3.5 2704.94    11.8 2702.83    20.1  2702.1    24.1 2701.06
    30.6 2698.28    33.9 2697.33    37.1 2697.08      45  2698.7    49.1 2698.24
    57.4 2695.73    69.9 2689.12      74 2688.17    86.5 2687.67    90.6  2686.6
    97.32683.947    98.9 2683.35   103.1 2683.03   110.6 2683.96   115.6 2684.83
   119.7 2686.23   123.9 2688.97   132.2  2695.6   136.3 2698.22   144.6 2701.39
   148.8  2701.9   152.9 2701.74   165.4 2700.22   173.6 2700.88   204.7 2701.84
#Mann= 3 ,-1,0
       0      .1       0    97.3    .045       0   110.6      .1       0
Bank Sta=97.3,110.6
XS Rating Curve= 0 ,0
Exp/Cntr=0.3,0.1

Type RM Length L Ch R = 1 ,2589    ,203.8,203.9,204.1
XS GIS Cut Line= 2
 2220403.6499625616322.3092662042220284.42003298616586.782928053
#Sta/Elev= 30
       0 2707.78    37.7 2705.88    55.8 2703.83    65.3 2701.29    77.4 2700.54
    83.4 2698.32   113.7 2689.08   125.8 2684.77   134.8 2680.94   147.9 2677.79
   152.3 2677.12   161.1 2678.33   165.5 2678.14   171.1 2678.68   174.2 2678.46
   178.22676.587     183 2675.68   187.4 2675.94   189.3 2676.61   196.2 2679.74
   209.4 2679.67   213.8 2680.73   235.7 2696.51   248.9 2706.77   253.2 2709.06
   257.6 2710.45   264.9 2713.74   270.8 2715.84   279.6    2717   290.1 2714.44
#Mann= 4 ,-1,0
       0      .1       0   178.2    .045       0   189.3      .1       0
     250     .03       0
Bank Sta=178.2,189.3
XS Rating Curve= 0 ,0
Exp/Cntr(USF)=0,0
Exp/Cntr=0.3,0.1

Type RM Length L Ch R = 1 ,2385    ,233.4,233.9,232.9
XS GIS Cut Line= 2
2220247.56714567616191.1563437292220101.23950489616503.321977387
#Sta/Elev= 30
       0 2706.34     6.7 2706.01    11.1 2704.38    22.1 2695.28    34.1 2687.62
    55.2 2677.81    64.2 2674.75   108.3 2670.16   121.5 2671.16   130.2 2670.09
   142.4 2667.65   166.5 2670.64   193.6 2670.92   199.6 2669.66   205.9 2665.77
   209.9 2664.98     2162665.776   227.5 2667.93   235.7  2668.6     254 2667.24
   267.3 2668.54   271.7 2668.28   289.4  2672.4   301.8 2677.55   307.1 2680.64
   316.9 2689.29   328.4 2700.85   333.6  2705.1   337.9 2706.87   344.8 2708.18
#Mann= 4 ,-1,0
       0      .1       0   205.9    .045       0     216      .1       0
     290     .06       0
#XS Ineff= 2 , 0
          165.61 2674.24  236.18         2670.98
Permanent Ineff=
       F       F
Bank Sta=205.9,216
XS Rating Curve= 0 ,0
Exp/Cntr(USF)=0,0
Exp/Cntr=0.3,0.1

Type RM Length L Ch R = 1 ,2152    ,121.6,127.2,130.4
XS GIS Cut Line= 2
2220003.68774437616148.8839141712219901.80035005616422.028843622
#Sta/Elev= 30
       0    2685    12.3 2682.76      43 2678.58    72.9 2676.72    77.2 2675.38
      90 2667.05   102.8 2663.47   119.9  2662.6   136.9 2660.35   149.1  2660.6
     154 2661.21   162.5 2660.83   167.8 2659.63   170.9 2658.13   175.4 2655.05
   179.6 2654.44   186.32655.054     201 2658.38   214.4 2658.66     218 2659.38
   222.3 2661.63   226.8 2663.19   230.9 2663.94   239.4 2664.17   242.4 2664.91
   250.4 2669.36   260.7 2671.01   269.3 2674.89   282.1 2679.46   291.5  2684.6
#Mann= 4 ,-1,0
       0      .1       0   175.4    .045       0   186.3      .1       0
     220     .06       0
Bank Sta=175.4,186.3
XS Rating Curve= 0 ,0
Exp/Cntr(USF)=0,0
Exp/Cntr=0.3,0.1

Type RM Length L Ch R = 1 ,2024    ,173.9,170.1,164.2
XS GIS Cut Line= 4
 2219977.0552424616131.084103288 2219870.8213752616247.853560629
2219797.07224425616262.7789799882219706.64176224616324.236589115
#Sta/Elev= 30
       0 2690.78     4.9 2688.08    13.2 2684.64    47.4 2679.38    66.7 2674.05
    73.1 2673.15    78.6 2673.41    83.9  2672.4    94.8  2668.3   100.2 2664.57
   105.6 2661.87   116.4    2664   164.6 2660.44   171.4 2659.49   176.9 2657.08
  185.782650.014   189.1 2649.02   193.2 2649.47     1942650.042   201.4 2654.94
   209.5 2658.25   222.3 2659.24   258.7  2660.5   301.7  2661.1   307.5 2661.96
   311.6 2663.23   321.2 2668.96   322.8 2669.35   327.6 2669.67   342.4 2668.55
#Mann= 5 ,-1,0
       0      .1       0  185.78    .045       0     194      .1       0
  197.86     .06       0  313.11      .1       0
Bank Sta=185.78,194
XS Rating Curve= 0 ,0
Exp/Cntr(USF)=0,0
Exp/Cntr=0.3,0.1

Type RM Length L Ch R = 1 ,1854    ,250.2,255.7,253.5
XS GIS Cut Line= 2
2219815.88527603615985.558964932 2219668.4737268616316.151042244
#Sta/Elev= 30
       0 2688.18    25.9 2682.47    52.1 2679.21    66.1 2675.71    72.2 2673.31
    78.4 2669.95    87.2 2667.39    93.4  2664.9   104.7 2659.15   126.7 2646.19
   132.22643.617   135.8 2642.95   143.22643.586   148.5 2644.78   157.3 2644.34
   172.1 2646.52   184.3 2646.03   195.7 2649.04     201 2649.62   249.2 2649.58
     258 2650.96   271.1  2655.5   278.2 2656.77   301.8  2657.9   319.3 2658.11
   328.1 2659.55   336.8 2663.33   353.9 2663.46   358.7 2664.23     362 2663.46
#Mann= 3 ,-1,0
       0      .1       0   132.2    .045       0   143.2      .1       0
#XS Ineff= 2 , 0
                          178.21         2650.76
Permanent Ineff=
       F       F
Bank Sta=132.2,143.2
XS Rating Curve= 0 ,0
Exp/Cntr(USF)=0,0
Exp/Cntr=0.3,0.1

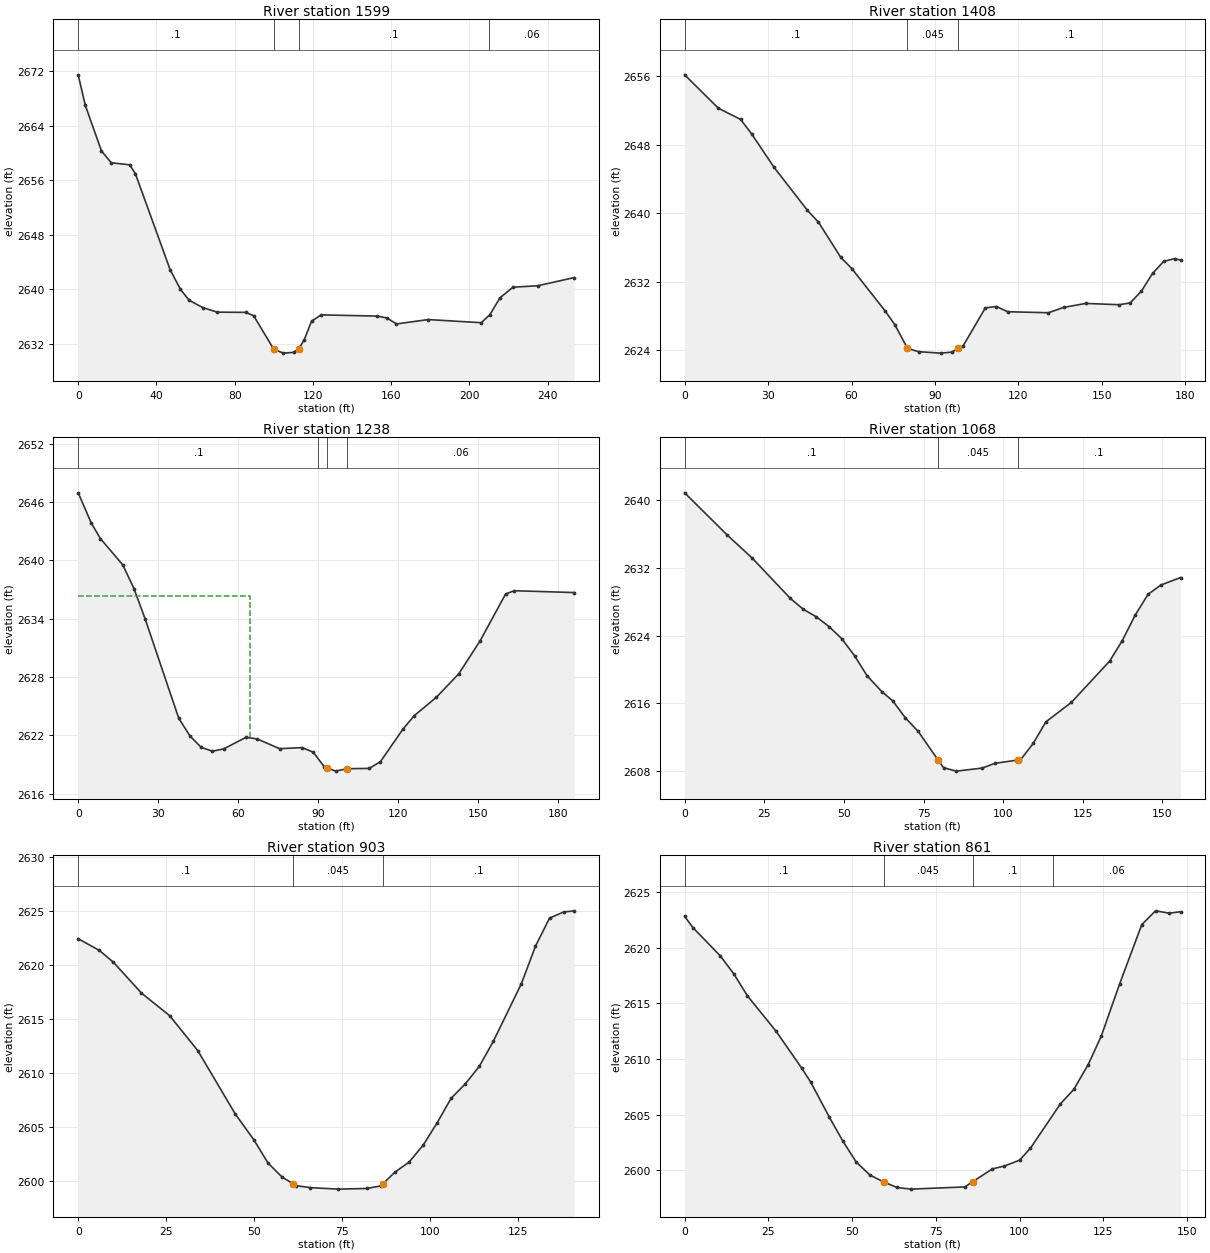
Type RM Length L Ch R = 1 ,1599    ,196.9,190.7,188.7
XS GIS Cut Line= 2
2219597.62914213615986.1619677292219456.11756375616196.553959965
#Sta/Elev= 30
       0 2671.49     3.6 2667.03    11.9  2660.3    16.9 2658.57    26.3 2658.27
    29.2 2656.99      47 2642.87    52.2    2640    56.7 2638.37    63.7 2637.29
    71.1 2636.62    85.6 2636.59    89.7  2636.1     100 2631.17   104.9  2630.6
   110.1 2630.71   112.7  2631.2   115.6 2632.57   119.3 2635.29   124.2 2636.22
     153 2636.04   157.9 2635.76   162.7 2634.89     179 2635.53   206.1 2635.07
   210.5 2636.25   215.7 2638.73   222.3 2640.29     235  2640.5   253.6  2641.7
#Mann= 4 ,-1,0
       0      .1       0     100    .045       0   112.7      .1       0
     210     .06       0
Bank Sta=100,112.7
XS Rating Curve= 0 ,0
Exp/Cntr=0.3,0.1

Type RM Length L Ch R = 1 ,1408    ,169.7,169.9,171
XS GIS Cut Line= 2
2219349.08650556615961.1039908772219355.10821917616139.346713799
#Sta/Elev= 30
       0 2656.16    12.1 2652.26    20.1 2650.95    24.1 2649.24    32.1 2645.36
    44.1 2640.33    48.1 2638.94    56.1 2634.83    60.1 2633.51    72.1 2628.55
    75.6 2626.93    80.1 2624.18    84.1  2623.8    92.1 2623.63    96.1 2623.75
   98.29 2624.18   100.1 2624.47   108.1 2628.92   112.1 2629.08   116.1 2628.47
   130.8 2628.35   136.2 2628.97   144.2 2629.44   156.2 2629.29   160.2  2629.5
   164.2 2630.88   168.2 2632.94   172.2 2634.35   176.2 2634.68   178.3  2634.5
#Mann= 3 ,-1,0
       0      .1       0    80.1    .045       0   98.29      .1       0
Bank Sta=80.1,98.29
XS Rating Curve= 0 ,0
Exp/Cntr(USF)=0,0
Exp/Cntr=0.3,0.1

Type RM Length L Ch R = 1 ,1238    ,171.9,170.1,167.9
XS GIS Cut Line= 2
2219213.66485722615977.2957097012219157.06074926  616154.3340899
#Sta/Elev= 30
       0 2646.95     4.9 2643.84     8.3 2642.25    16.7 2639.54    20.9  2637.1
    25.1 2633.97    37.7 2623.75    41.9 2621.93    46.1 2620.77    50.3 2620.37
    54.5  2620.6    62.9  2621.8    67.1 2621.63    75.5 2620.63    83.9 2620.74
    88.1 2620.27    92.3 2618.74    93.4 2618.65    96.5 2618.32   100.7 2618.57
   109.1  2618.6   113.3  2619.3   121.7 2622.63   125.9 2624.01   134.3 2625.93
   142.7 2628.35   150.7 2631.75   160.2 2636.54   163.4 2636.88   185.9 2636.69
#Mann= 4 ,-1,0
       0      .1       0      90     .06       0    93.4    .045       0
   100.7     .06       0
#XS Ineff= 2 , 0
           64.39 2636.37
Permanent Ineff=
       F       F
Bank Sta=93.4,100.7
XS Rating Curve= 0 ,0
Exp/Cntr(USF)=0,0
Exp/Cntr=0.3,0.1

Type RM Length L Ch R = 1 ,1068    ,164.8,164.7,164.6
XS GIS Cut Line= 2
2219023.37870707 615952.004512532219013.74396529616107.364723725
#Sta/Elev= 30
       0 2640.84    13.2 2635.92    21.2 2633.14    33.2 2628.38    37.2 2627.11
    41.3 2626.22    45.3 2625.07    49.3 2623.64    53.4 2621.59    57.3 2619.24
    61.9 2617.39    65.3 2616.31    69.3 2614.29    73.3  2612.7    79.6  2609.3
    81.3 2608.41    85.3 2608.01    93.4 2608.37    97.4 2608.93   104.6 2609.32
   105.4 2609.33   109.4 2611.27   113.4 2613.82   121.4 2616.12   133.4 2620.98
   137.4 2623.41   141.4 2626.39   145.5 2628.88   149.5 2629.96   155.7 2630.85
#Mann= 3 ,-1,0
       0      .1       0    79.6    .045       0   104.6      .1       0
Bank Sta=79.6,104.6
XS Rating Curve= 0 ,0
Exp/Cntr(USF)=0,0
Exp/Cntr=0.3,0.1

Type RM Length L Ch R = 1 ,903     ,40.6,42.4,43.7
XS GIS Cut Line= 2
2218857.17941137615959.2305688652218849.95335504616100.138667391
#Sta/Elev= 30
       0 2622.45       6 2621.37      10 2620.28      18 2617.42      26 2615.34
      34 2612.11    44.7 2606.23      50 2603.84      54  2601.7      58 2600.41
      61 2599.81      62 2599.61      66 2599.43      74 2599.29    82.1 2599.35
    86.1 2599.59    86.6 2599.75    90.1 2600.86    94.1 2601.78    98.1 2603.34
   102.1 2605.41   106.1  2607.7   110.1 2609.01   114.1 2610.64   118.1 2612.96
   126.1  2618.3   130.1 2621.76   134.1 2624.36   138.1 2624.92   141.1 2625.03
#Mann= 3 ,-1,0
       0      .1       0      61    .045       0    86.6      .1       0
Bank Sta=61,86.6
XS Rating Curve= 0 ,0
Exp/Cntr(USF)=0,0
Exp/Cntr=0.3,0.1

Type RM Length L Ch R = 1 ,861     ,132.8,135.6,136.7
XS GIS Cut Line= 2
2218825.41166803615950.7354244962218799.51013641616096.524045306
#Sta/Elev= 30
       0 2622.82     2.5 2621.81    10.6 2619.29    14.7 2617.65    18.7  2615.7
    27.3  2612.5      35 2609.16    37.7 2607.89    43.1 2604.83    47.2 2602.64
    51.2 2600.75    55.3 2599.57    59.4 2598.95    63.4 2598.45    67.5  2598.3
    83.7  2598.5      86 2598.97    91.9 2600.12    95.4 2600.37     100  2600.9
   103.2 2601.96   112.2 2605.97   116.2 2607.27   120.5  2609.5   124.4 2612.06
   129.9 2616.77   136.5 2622.09   140.6 2623.33   144.7 2623.12   148.1 2623.25
#Mann= 4 ,-1,0
       0      .1       0    59.4    .045       0      86      .1       0
     110     .06       0
Bank Sta=59.4,86
XS Rating Curve= 0 ,0
Exp/Cntr(USF)=0,0
Exp/Cntr=0.3,0.1

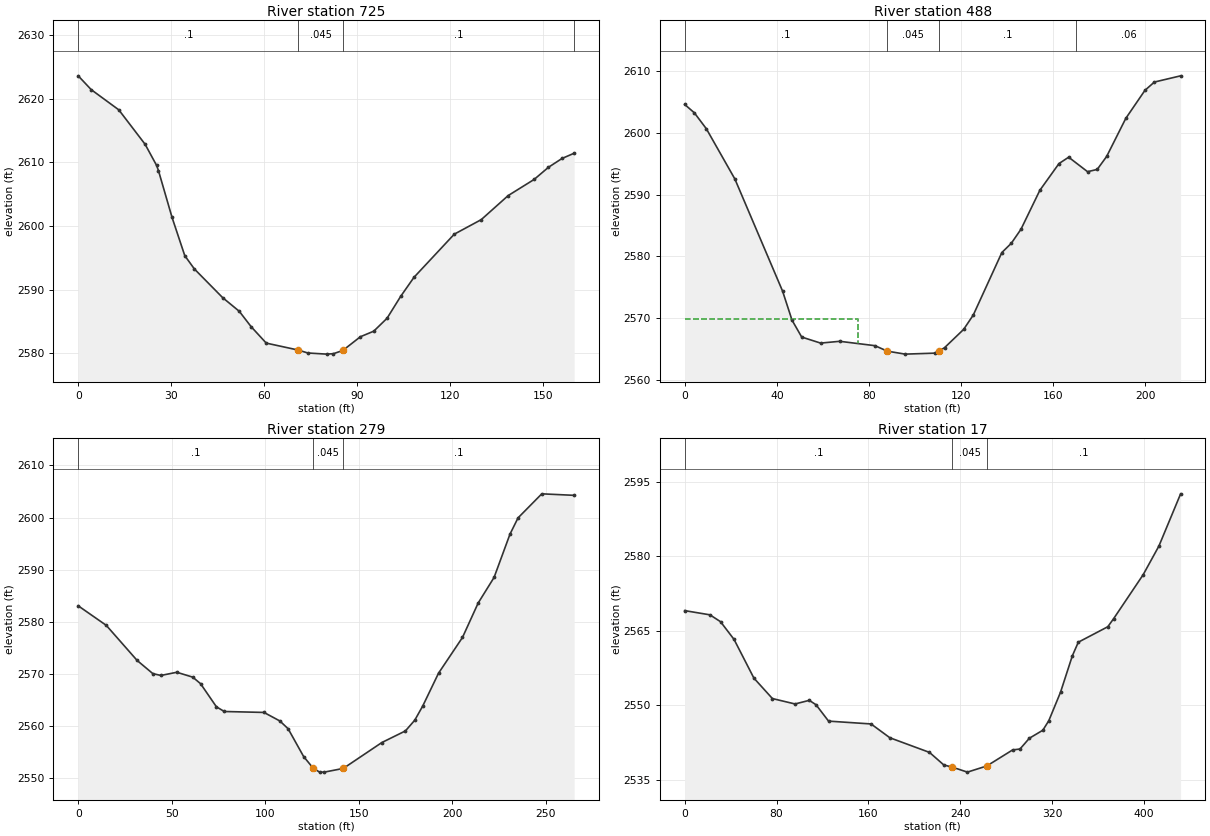
Type RM Length L Ch R = 1 ,725     ,240.6,237.3,226.8
XS GIS Cut Line= 2
 2218713.3787963615917.2832123072218651.16719011616064.747760321
#Sta/Elev= 30
       0 2623.56     4.2 2621.39    13.1 2618.22    21.6 2612.81    25.3  2609.5
    25.9 2608.69    30.3 2601.32    34.4 2595.33    37.5 2593.24    46.6 2588.75
      52 2586.59    55.8 2584.19    60.7  2581.6    71.1  2580.5    74.1 2580.05
    80.2 2579.87    82.4 2579.94    85.4 2580.44    91.1  2582.6    95.4 2583.47
    99.7  2585.5   104.1 2588.94   108.4 2591.93   121.4  2598.7   130.1 2600.98
   138.8 2604.76   147.2  2607.3   151.8  2609.2   156.2 2610.59   160.1 2611.41
#Mann= 4 ,-1,0
       0      .1       0    71.1    .045       0    85.4      .1       0
     160     .06       0
Bank Sta=71.1,85.4
XS Rating Curve= 0 ,0
Exp/Cntr(USF)=0,0
Exp/Cntr=0.3,0.1

Type RM Length L Ch R = 1 ,488     ,209.1,209.3,205.7
XS GIS Cut Line= 2
 2218440.1277337615892.1313598432218495.48221455616100.165071812
#Sta/Elev= 30
       0 2604.65     4.2 2603.29     9.4 2600.71    21.8 2592.55    42.5 2574.37
    46.6 2569.66    50.8 2566.92      59 2565.94    67.3 2566.23    82.6 2565.52
      88 2564.63    95.7 2564.15   108.7 2564.31   110.5 2564.67   112.8 2565.19
   121.1 2568.16   125.3  2570.5   137.7 2580.63   141.8 2582.13     146 2584.41
   154.2 2590.73   162.5 2595.06   166.7 2596.09   174.9 2593.74   179.1 2594.11
   183.2 2596.22   191.5 2602.39   199.8 2606.93   203.9 2608.28   215.3 2609.29
#Mann= 4 ,-1,0
       0      .1       0      88    .045       0   110.5      .1       0
     170     .06       0
#XS Ineff= 2 , 0
            75.2 2569.85
Permanent Ineff=
       F       F
Bank Sta=88,110.5
XS Rating Curve= 0 ,0
Exp/Cntr=0.3,0.1

Type RM Length L Ch R = 1 ,279     ,252.4,261.4,268.2
XS GIS Cut Line= 2
2218242.75250693615963.509674852 2218330.9386976616213.559903781
#Sta/Elev= 30
       0 2583.05      15  2579.3    31.5 2572.56    39.9 2570.03    44.2 2569.68
    52.7 2570.29    61.2 2569.36    65.4  2568.1    73.9 2563.65    78.1 2562.76
    99.3 2562.58   107.8 2560.94   112.2 2559.45   120.5 2554.11   125.62551.877
     129 2551.13   131.5 2551.12   141.7 2551.83   162.3  2556.8   174.9 2559.03
   179.9 2561.09   184.2 2563.84   192.6 2570.11   205.4 2576.97   213.8 2583.59
   222.3  2588.5   230.8 2596.81   235.1 2599.93   247.8 2604.55   265.1 2604.26
#Mann= 3 ,-1,0
       0      .1       0   125.6    .045       0   141.7      .1       0
Bank Sta=125.6,141.7
XS Rating Curve= 0 ,0
Exp/Cntr(USF)=0,0
Exp/Cntr=0.3,0.1

Type RM Length L Ch R = 1 ,17      ,,,
XS GIS Cut Line= 4
2218216.33168073616008.0636150222218050.35866352616160.979922929
 2218042.3534927616204.5305946192218144.07125874 616330.57637781
#Sta/Elev= 30
       0 2569.07      22 2568.22    31.2 2566.84      43 2563.26    60.3 2555.45
    76.4 2551.33    96.1 2550.24   108.5 2550.97   114.4 2550.08   125.3 2546.78
   162.3 2546.21   178.7 2543.42   213.2 2540.47   225.7 2537.93   233.2 2537.49
   246.2 2536.49   263.1 2537.73   285.6 2540.97     292 2541.15   300.2 2543.33
   311.9 2544.94   317.1 2546.86   327.3  2552.6   337.6 2559.95   342.8  2562.7
   368.5 2565.82   373.6 2567.46   399.3 2576.32     413  2582.1   431.9 2592.63
#Mann= 3 ,-1,0
       0      .1       0   233.2    .045       0   263.1      .1       0
#XS Ineff= 2 , 0
          173.17 2544.05
Permanent Ineff=
       F       F
Bank Sta=233.2,263.1
XS Rating Curve= 0 ,0
Exp/Cntr(USF)=0,0
Exp/Cntr=0.3,0.1
LCMann Table=0

Chan Stop Cuts=-1
Use User Specified Reach Order=0
Composite Channel Slope=5